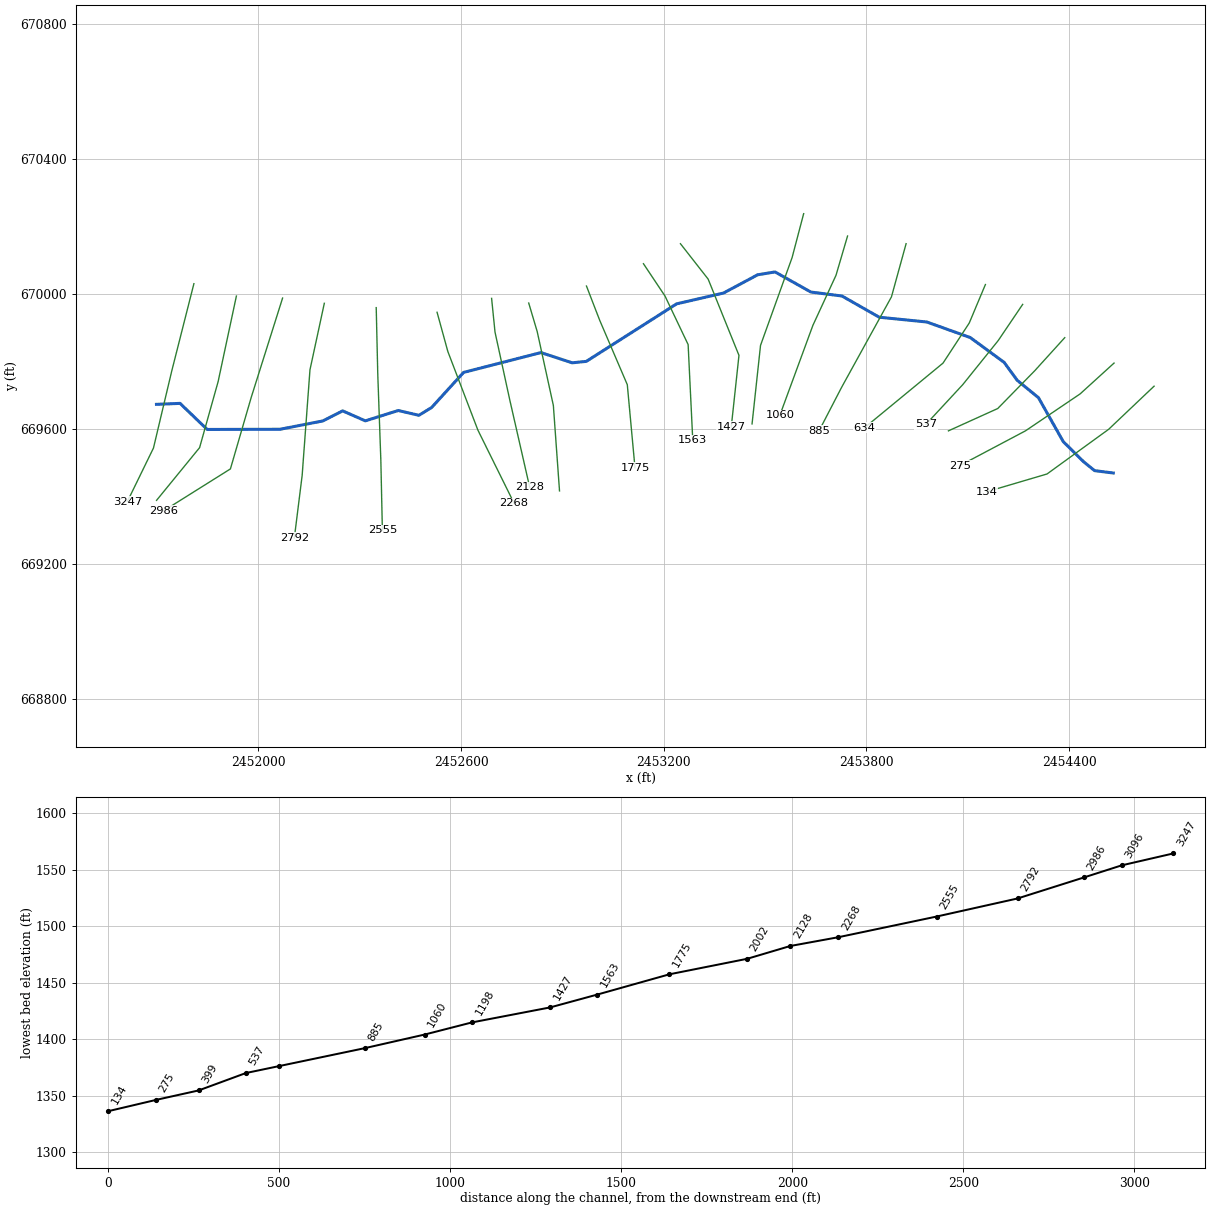
--- SBPOTOMC_T3.prj (project) ---

Proj Title=SBPOTOMC_T3
Current Plan=p01
Default Exp/Contr=0,0
English Units
Geom File=g01
Flow File=f01
Plan File=p01
BEGIN DESCRIPTION:
Stream Name:South Branch Potomac River Tributary 3
Flood Zone: Zone A
Pendleton County, WV
WVDHSEM Flood Warning & Analysis Mapping
HEC-RAS Version: 5.0.7
Hydrology Method:
Regression
Model Notes:
Tie in with SBPOTOMC at the downstream end.
END DESCRIPTION:
DSS Export Rating Curves= 0
DSS Export Rating Curve Sorted= 0
DSS Export Volume Flow Curves= 0
DXF OffsetX= 0
DXF OffsetY= 0
DXF ScaleX= 0
DXF ScaleY= 0

--- SBPOTOMC_T3.p01 (plan) ---

Plan Title=Floodplain
Program Version=5.07
Short Identifier=Floodplain
Geom File=g01
Flow File=f01
Subcritical Flow
K Sum by GR= 0
Std Step Tol= 0.01
Critical Tol= 0.01
Num of Std Step Trials= 20
Max Error Tol= 0.3
Flow Tol Ratio= 0.001
Split Flow NTrial= 30
Split Flow Tol= 0.02
Split Flow Ratio= 0.02
Log Output Level= 0
Friction Slope Method= 1
Unsteady Friction Slope Method= 2
Unsteady Bridges Friction Slope Method= 1
Parabolic Critical Depth
Global Vel Dist= 0 , 0 , 0
Global Log Level= 0
CheckData=True
Encroach Param=-1 ,0,0, 0
Mapping Interval=1HOUR
Computation Time Step Use Courant=        0
Computation Time Step Use Time Series=    0
Computation Time Step Count To Double=0
Computation Time Step Max Doubling=0
Computation Time Step Max Halving=0
Computation Time Step Residence Courant=0
Run HTab= 0
Run UNet= 0
Run Sediment= 0
Run PostProcess= 0
Run WQNet= 0
Run RASMapper= 0
UNET Theta= 0
UNET Theta Warmup= 0
UNET ZTol= 0
UNET ZSATol= 0
UNET MxIter= 0
UNET Max Iter WO Improvement= 0
UNET MaxInSteps= 0
UNET DtIC= 0
UNET DtMin= 0
UNET MaxCRTS= 0
UNET WFStab= 0
UNET SFStab= 0
UNET WFX= 1
UNET SFX= 1
UNET 1D Methodology=Finite Difference
UNET DSS MLevel= 1
UNET Pardiso=0
UNET DZMax Abort= 0
UNET Use Existing IB Tables= 0
UNET Froude Reduction=False
UNET Froude Limit= 0
UNET Froude Power= 0
UNET D1 Cores= 0
UNET D2 Coriolis=0
UNET D2 Cores= 0
UNET D2 Theta= 1
UNET D2 Theta Warmup= 1
UNET D2 Z Tol= 0.01
UNET D2 Volume Tol= 0.01
UNET D2 Max Iterations= 20
UNET D2 Equation= 0
UNET D2 RampUpFraction=0.1
UNET D2 TimeSlices= 1
UNET D2 BCVolumeCheck=0
UNET D1D2 MaxIter= 0
UNET D1D2 ZTol=0.01
UNET D1D2 QTol=0.1
UNET D1D2 MinQTol=1
Write IC File= 0
Write IC File at Fixed DateTime=0
Write IC File at Sim End=0
Echo Input=False
Echo Parameters=False
Echo Output=False
Write Detailed= 0
HDF Write Warmup=0
HDF Write Time Slices=0
HDF Flush=0
HDF Face Node Velocities=0
HDF Compression= 1
HDF Chunk Size= 1
HDF Spatial Parts= 1
HDF Use Max Rows=0
HDF Fixed Rows= 1
Calibration Method= 0
Calibration Iterations= 20
Calibration Max Change=0.05
Calibration Tolerance=0.2
Calibration Maximum=1.5
Calibration Minimum=0.5
Calibration Optimization Method= 1
WQ AD Non Conservative
WQ ULTIMATE=-1
WQ Max Comp Step=1HOUR
WQ Output Interval=15MIN
WQ Output Selected Increments= 0
WQ Output face flow=0
WQ Output face velocity=0
WQ Output face area=0
WQ Output face dispersion=0
WQ Output cell volume=0
WQ Output cell surface area=0
WQ Output cell continuity=0
WQ Output cumulative cell continuity=0
WQ Output face conc=0
WQ Output face dconc_dx=0
WQ Output face courant=0
WQ Output face peclet=0
WQ Output face adv mass=0
WQ Output face disp mass=0
WQ Output cell mass=0
WQ Output cell source sink temp=0
WQ Output nsm pathways=0
WQ Output nsm derived pathways=0
WQ Output MaxMinRange=-1
WQ Daily Max Min Mean=-1
WQ Daily Range=0
WQ Daily Time=0
WQ Create Restart=0
WQ Fixed Restart=0
WQ System Summary=0
WQ Write To DSS=0
WQ Use Fixed Temperature=0
Sorting and Armoring Iterations= 10
XS Update Threshold= 0.02
Bed Roughness Predictor= 0
Hydraulics Update Threshold= 0.02
Energy Slope Method= 1
Volume Change Method= 1
Sediment Retention Method= 0
XS Weighting Method= 0
Number of US Weighted Cross Sections= 1
Number of DS Weighted Cross Sections= 1
Upstream XS Weight=0
Main XS Weight=1
Downstream XS Weight=0
Number of DS XS's Weighted with US Boundary= 1
Upstream Boundary Weight= 1
Weight of XSs Associated with US Boundary= 0
Number of US XS's Weighted with DS Boundary= 1
Downstream Boundary Weight= 0.5
Weight of XSs Associated with DS Boundary= 0.5
Percentile Method= 0
Sediment Output Level= 3
Mass or Volume Output= 0
Output Increment Type= 1
Profile and TS Output Increment= 1
XS Output Flag= 0
XS Output Increment= 10
Write Gradation File= 0
Read Gradation Hotstart= 0
Write HDF5 File= 1
Write Binary Output= 1
Write DSS Sediment File= 0
SV Curve= 0
Specific Gage Flag= 0

--- SBPOTOMC_T3.f01 (steady flow) ---

Flow Title=Flows
Program Version=5.07
Number of Profiles= 6
Profile Names=P100yr,P10yr,P25yr,P50yr,P500yr,P101yr
River Rch & RM=SBPOTOMC_T3,Main            ,3247
     336     159     223     278     490     409
River Rch & RM=SBPOTOMC_T3,Main            ,2792
     568     266     375     469     832     691
River Rch & RM=SBPOTOMC_T3,Main            ,1198
     805     375     531     664    1184     979
Boundary for River Rch & Prof#=SBPOTOMC_T3,Main            , 1
Up Type= 0
Dn Type= 3
Dn Slope=0.07137
Boundary for River Rch & Prof#=SBPOTOMC_T3,Main            , 2
Up Type= 0
Dn Type= 3
Dn Slope=0.07137
Boundary for River Rch & Prof#=SBPOTOMC_T3,Main            , 3
Up Type= 0
Dn Type= 3
Dn Slope=0.07137
Boundary for River Rch & Prof#=SBPOTOMC_T3,Main            , 4
Up Type= 0
Dn Type= 3
Dn Slope=0.07137
Boundary for River Rch & Prof#=SBPOTOMC_T3,Main            , 5
Up Type= 0
Dn Type= 3
Dn Slope=0.07137
Boundary for River Rch & Prof#=SBPOTOMC_T3,Main            , 6
Up Type= 0
Dn Type= 3
Dn Slope=0.07137
DSS Import GetInterval= 0
DSS Import GetPeak= 0
DSS Import FillOption= 0

--- SBPOTOMC_T3.g01 (geometry) ---

Geom Title=Geometry
Program Version=5.07

River Reach=SBPOTOMC_T3     ,Main
Reach XY= 30
     2451698.457      669673.351     2451768.295      669676.213
     2451848.579      669599.031     2452064.404      669599.575
      2452190.53      669624.102     2452249.642      669653.998
     2452316.772      669624.492     2452414.108      669655.095
     2452475.353      669640.897     2452513.013      669664.004
     2452607.617      669767.869     2452836.673      669826.602
     2452929.101      669796.271     2452970.861      669800.505
     2453238.367      669970.903     2453377.383      670002.951
     2453478.162      670056.889     2453529.628      670065.297
     2453635.609      670005.813      2453727.78      669994.086
     2453837.951      669931.298     2453979.253      669917.034
     2454107.603      669871.046     2454207.722      669797.668
     2454246.501      669744.563     2454309.374       669693.11
     2454382.912       669562.83     2454443.326      669503.238
     2454475.488      669477.082     2454530.945      669470.085

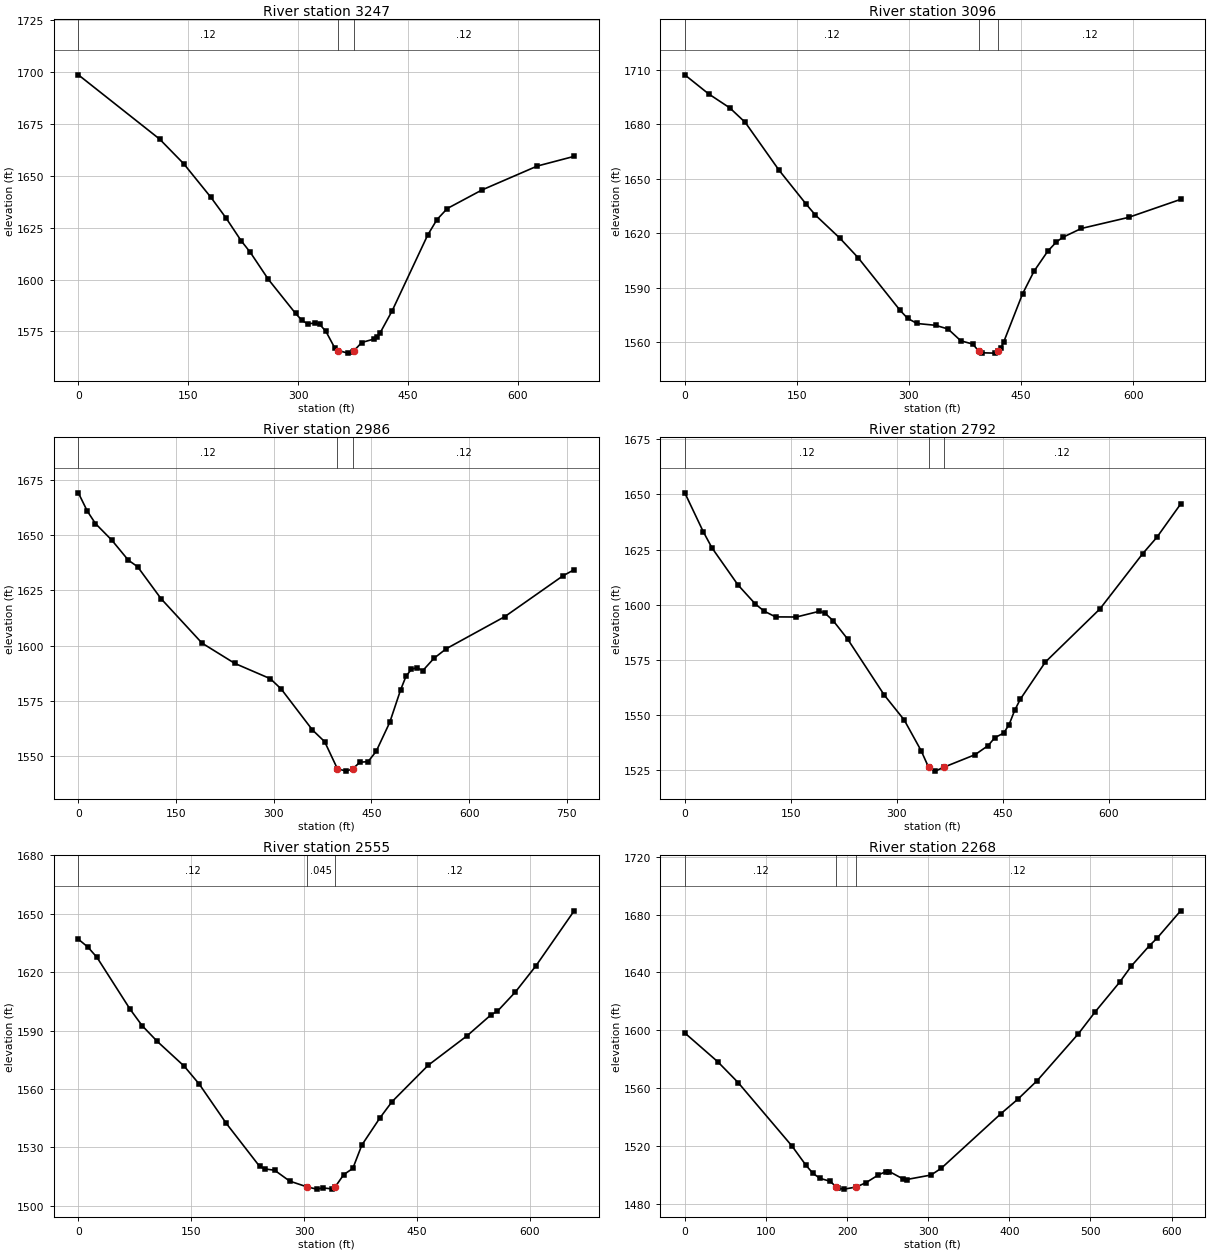
Type RM Length L Ch R = 1 ,3247    ,150.1,151.4,152.9
XS GIS Cut Line= 4
2451809.26132745670030.4565063882451743.62415607669771.768830915
2451689.57001492669543.9692360952451612.34981329669385.667822746
#Sta/Elev= 30
       0 1698.57     111 1667.63     144 1655.72   181.1 1639.56   201.8 1629.58
   222.2 1618.75   234.8 1613.11   259.5 1600.08   296.6 1583.71   305.3 1580.38
     313 1578.64   322.7 1579.05   329.5 1578.45   338.1 1575.04     350 1567.18
  355.05 1565.81     368 1564.56   374.7 1565.03   376.71565.812     387 1569.67
   403.5 1571.32   407.6 1572.16   411.7 1574.03   428.6 1584.94   477.1 1621.41
   489.8 1628.88   503.9  1634.2   551.2 1643.12   626.8 1654.65677.1414 1659.31
#Mann= 3 , 0 , 0
       0     .12       0  355.05    .045       0   376.7     .12       0
Bank Sta=355.05,376.7
XS Rating Curve= 0 ,0
Exp/Cntr(USF)=0,0
Exp/Cntr=0.3,0.1

Type RM Length L Ch R = 1 ,3096    ,111,109.9,109.3
XS GIS Cut Line= 4
 2451935.0582341669993.9772974262451880.98185201669740.590821337
2451826.13295017 669545.143326062451698.66719238669389.094337736
#Sta/Elev= 30
       0 1707.23    31.8 1696.76    60.2 1689.03    80.9 1681.03   125.9 1654.83
   162.7 1635.87   174.9 1629.95   207.7 1617.21   232.1 1606.46   288.2  1577.5
   298.2 1573.14   310.7 1570.29   335.6 1569.29   352.3 1567.26   369.3 1560.79
   385.5 1558.93  393.371555.073     398 1554.15   414.6 1553.97   419.51555.069
   422.9 1556.62     427  1560.3     452 1586.57   467.4 1599.08   485.7 1610.06
   497.4 1615.23   506.3 1617.83   530.7 1622.62   593.9 1628.72   663.6 1638.64
#Mann= 3 , 0 , 0
       0     .12       0  393.37    .045       0   419.5     .12       0
Bank Sta=393.37,419.5
XS Rating Curve= 0 ,0
Exp/Cntr(USF)=0,0
Exp/Cntr=0.3,0.1

Type RM Length L Ch R = 1 ,2986    ,193.2,194.4,194.4
XS GIS Cut Line= 4
2452071.81001301 669987.985395492451979.14577105669694.548629281
2451917.36960974669482.1930747882451720.45809558669358.640752174
#Sta/Elev= 30
       0 1669.12    13.7 1660.89    26.3 1655.22    51.5 1647.69    76.7 1638.69
      91 1635.71     127 1621.26   189.9 1601.18   240.2 1592.01   294.8 1585.08
   311.5 1580.43   359.4 1561.94   378.2 1556.62   397.81544.375   411.5  1543.3
  421.571544.373   432.3 1547.34   444.8 1547.57   457.3 1552.22   478.2 1565.36
   494.8    1580   503.2 1586.23   511.5 1589.36   519.8 1590.09   528.9 1588.73
   546.1 1594.32     565 1598.64   654.8 1613.14   744.5 1631.67761.3427 1634.35
#Mann= 3 , 0 , 0
       0     .12       0   397.8    .045       0  421.57     .12       0
Bank Sta=397.8,421.57
XS Rating Curve= 0 ,0
Exp/Cntr(USF)=0,0
Exp/Cntr=0.3,0.1

Type RM Length L Ch R = 1 ,2792    ,228.5,236.5,231.4
XS GIS Cut Line= 4
2452195.36233562669972.5413551632452152.89122472669775.629840997
2452129.72516423 669462.888024382452106.55910374669277.559540459
#Sta/Elev= 30
       0  1650.7    26.2 1633.05    38.5 1625.75    75.3 1608.97    99.9 1600.32
   112.2 1597.13   128.5  1594.5   157.9 1594.45   189.9    1597   198.1 1596.29
   210.2 1592.71   230.3 1584.53   282.4 1559.07   310.5 1547.84   334.5 1533.91
  345.041526.401   354.6 1524.64  366.561526.401   410.8 1532.08   429.5 1536.24
   438.8 1539.81   451.2 1541.83   458.9 1545.62   466.9 1552.15   474.9 1557.22
   510.3 1574.03   587.6 1598.12   648.1 1623.13   668.1 1630.52701.8091 1645.62
#Mann= 3 , 0 , 0
       0     .12       0  345.04    .045       0  366.56     .12       0
Bank Sta=345.04,366.56
XS Rating Curve= 0 ,0
Exp/Cntr(USF)=0,0
Exp/Cntr=0.3,0.1

Type RM Length L Ch R = 1 ,2555    ,287,287.1,285.2
XS GIS Cut Line= 4
2452348.99157928669959.6655815232452353.55135497669763.595227013
2452362.67090634669508.2477885812452367.23068203669300.777994856
#Sta/Elev= 30
       0 1636.89    12.8  1632.8    24.8 1627.54    68.8 1600.95    84.8 1592.52
   104.8 1584.48   140.8  1571.7   160.8 1562.49   196.8 1542.31   240.9 1520.35
   248.2 1518.97   260.9 1518.34   280.9 1512.76  303.931509.798   316.9 1508.63
   324.9 1509.27   336.9 1508.76  341.48  1509.8   352.9 1516.11   364.9 1519.25
   376.9 1531.25     401 1545.21     417 1553.49   465.2 1572.22     517 1587.38
     549  1598.2     557 1599.86     581 1609.77   608.4 1623.24659.1535 1651.44
#Mann= 3 , 0 , 0
       0     .12       0  303.93    .045       0  341.48     .12       0
Bank Sta=303.93,341.48
XS Rating Curve= 0 ,0
Exp/Cntr(USF)=0,0
Exp/Cntr=0.3,0.1

Type RM Length L Ch R = 1 ,2268    ,139.5,140.4,138.1
XS GIS Cut Line= 4
2452529.10271889669945.9862544642452561.02114869669829.711974464
2452649.93677458669597.163414464 2452757.0915032669380.574069366
#Sta/Elev= 30
       0 1598.21    40.5  1578.4    65.7 1563.97   132.2 1520.05   149.3 1506.86
   157.9 1501.25   166.4 1497.84   179.3 1495.71  186.721491.776   189.2 1490.88
   196.4 1490.33  211.171491.773   223.2 1494.74   238.7 1500.16   247.8 1502.42
   252.1  1502.5   269.2  1497.3   273.5 1496.98   303.5 1500.07   316.2 1504.76
   389.9 1542.57   410.7 1552.54   434.5 1565.35   485.3 1597.77   506.2 1613.03
   536.1 1633.33   550.6 1644.57   572.9 1658.62   581.8 1663.47611.1898 1682.58
#Mann= 3 , 0 , 0
       0     .12       0  186.72    .045       0  211.17     .12       0
Bank Sta=186.72,211.17
XS Rating Curve= 0 ,0
Exp/Cntr(USF)=0,0
Exp/Cntr=0.3,0.1

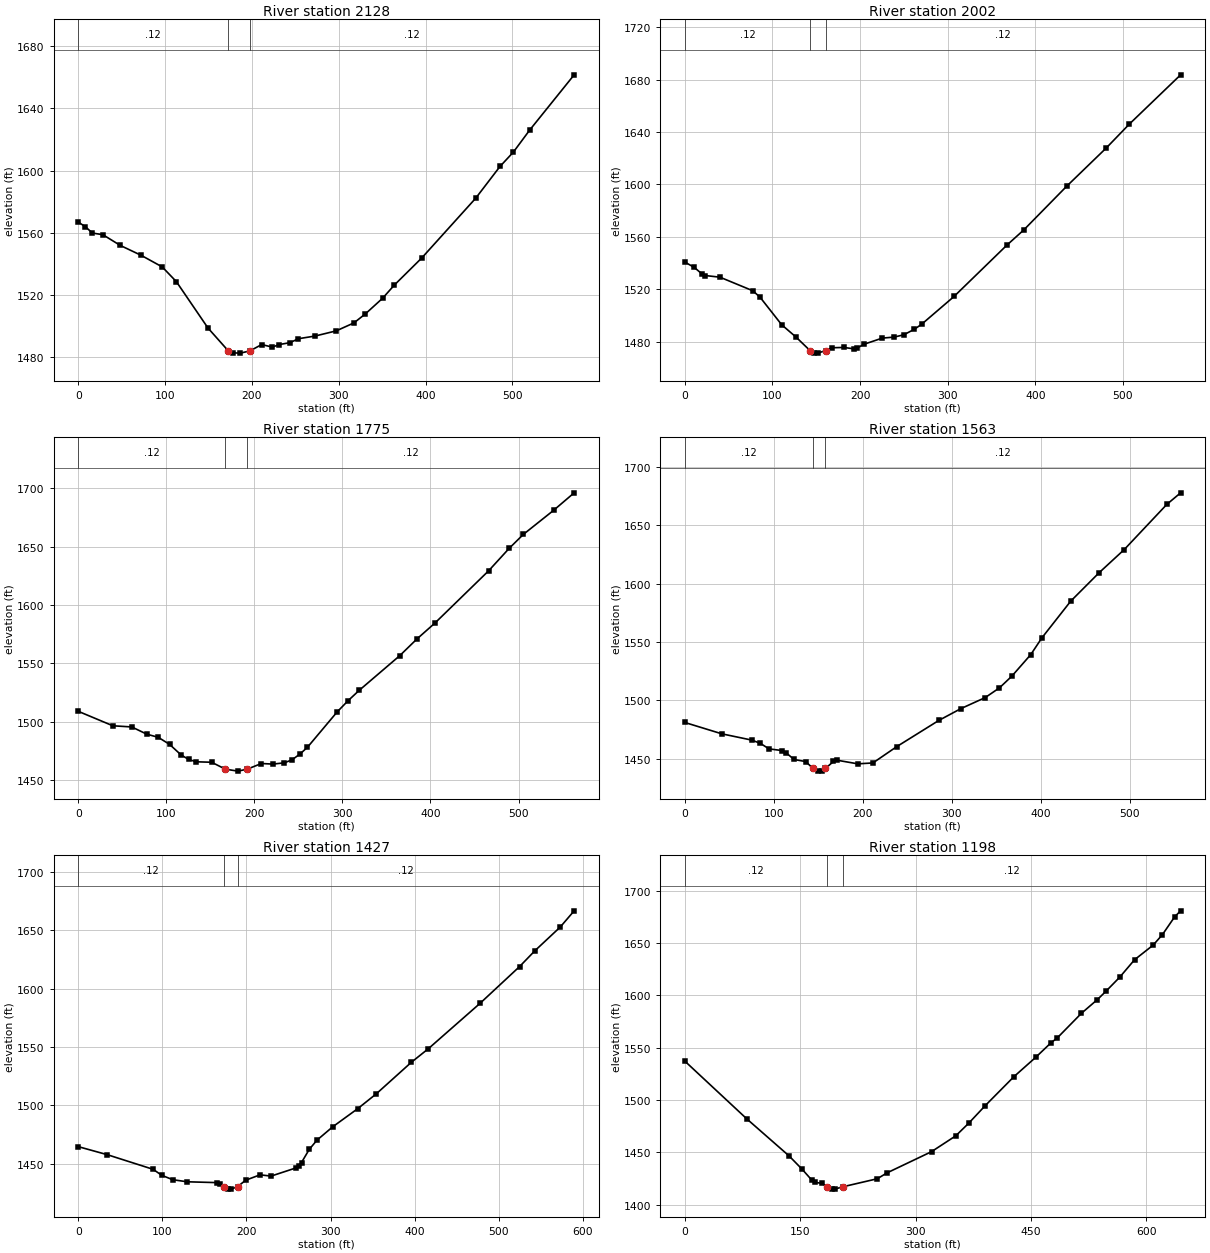
Type RM Length L Ch R = 1 ,2128    ,122.9,126,125
XS GIS Cut Line= 4
2452690.58254391669987.0246197292452700.62530058 669887.36957273
  2452744.658926669684.9693997562452803.37042656669427.720324945
#Sta/Elev= 30
       0 1566.86     8.2 1563.84    16.2 1559.83    28.3 1558.75    48.4 1551.84
    72.5 1545.46    96.6 1538.05   112.9 1528.58   149.4 1498.68  172.821483.976
   178.4 1482.73   186.6 1482.56  197.671483.976   211.2 1488.08   223.5 1486.43
   231.6 1488.09   243.9 1489.31   253.6 1491.84   272.6 1493.54   297.1 1496.88
   317.5 1502.01   330.8 1507.86   350.5 1517.86   364.2 1526.44   395.6 1543.77
   457.8 1582.25   485.8  1602.7   501.2 1611.92   519.9 1626.03   571.2 1661.63
#Mann= 3 , 0 , 0
       0     .12       0  172.82    .045       0  197.67     .12       0
Bank Sta=172.82,197.67
XS Rating Curve= 0 ,0
Exp/Cntr(USF)=0,0
Exp/Cntr=0.3,0.1

Type RM Length L Ch R = 1 ,2002    ,224.2,227.3,228.1
XS GIS Cut Line= 4
2452800.40937222669973.344908581 2452825.4881385669888.989058385
 2452873.3657832669670.1198254442452891.60488595669417.052274856
#Sta/Elev= 30
       0 1540.77    10.9 1536.61    19.3 1531.86    23.4 1530.46    40.1  1529.2
    77.7 1518.81      86  1513.8   110.6 1492.85     127 1483.42  142.881473.178
   147.5 1471.54   151.6 1471.22  160.871473.178   167.9 1475.32   181.5 1475.56
   192.5 1474.55   196.6 1475.13   204.8 1478.07   225.3 1482.68   238.6 1483.45
   249.8 1485.18   262.1  1489.5   270.3 1493.29   307.2 1514.46   367.4 1553.59
   386.9 1565.33   435.6 1598.53     481  1627.9   507.1 1645.98565.7735  1683.7
#Mann= 3 , 0 , 0
       0     .12       0  142.88    .045       0  160.87     .12       0
Bank Sta=142.88,160.87
XS Rating Curve= 0 ,0
Exp/Cntr(USF)=0,0
Exp/Cntr=0.3,0.1

Type RM Length L Ch R = 1 ,1775    ,209.8,212.1,211.2
XS GIS Cut Line= 4
2452971.40096046 670023.502441132453010.15905379669923.187376032
2453092.23501614669731.6767972092453115.03389458 669485.44891015
#Sta/Elev= 30
       0 1508.76    39.2 1496.38    60.7 1495.38    77.8 1489.16    90.7  1486.5
   103.6 1480.46   116.6 1471.45   125.3 1467.48     134 1465.49   151.4 1465.09
  167.051459.161   181.3 1457.48  191.811459.159     208 1464.02     221 1463.51
   234.1  1464.6   242.8 1467.23   251.5    1472   260.2  1477.9     294 1508.29
   306.2 1517.75   318.9  1526.7   364.9 1556.39   384.8 1570.98   405.1 1584.53
     466 1629.29   489.4  1648.6   505.5 1660.56   539.8 1681.17563.1805  1696.2
#Mann= 3 , 0 , 0
       0     .12       0  167.05    .045       0  191.81     .12       0
Bank Sta=167.05,191.81
XS Rating Curve= 0 ,0
Exp/Cntr(USF)=0,0
Exp/Cntr=0.3,0.1

Type RM Length L Ch R = 1 ,1563    ,136.7,136.5,136.3
XS GIS Cut Line= 4
2453140.11266085670089.6191885812453203.94952046669993.863899169
2453272.34615575669850.2309650522453286.02548281669567.524872503
#Sta/Elev= 30
       0 1481.07    41.7 1471.33    75.4 1465.96      85 1463.17    94.6 1458.47
     109 1457.06   113.5 1455.35   122.8 1449.38   136.1 1447.57  143.881441.724
   149.4 1439.42   153.8 1439.76  158.031441.722   167.1 1447.69   171.5 1448.71
   194.4 1445.66   211.4 1446.42     238  1460.3   285.5 1482.83   310.2  1492.9
   337.6 1502.38   353.6 1510.69   367.5 1520.69   388.8 1539.18   401.4  1553.6
   433.7 1584.92   465.7 1609.33   493.8 1629.05   541.8 1667.83557.2069 1677.65
#Mann= 3 , 0 , 0
       0     .12       0  143.88    .045       0  158.03     .12       0
Bank Sta=143.88,158.03
XS Rating Curve= 0 ,0
Exp/Cntr(USF)=0,0
Exp/Cntr=0.3,0.1

Type RM Length L Ch R = 1 ,1427    ,237.3,228.8,213.3
XS GIS Cut Line= 4
2453249.54727732670148.8962725032453331.62323967670044.021431718
 2453422.8187534669818.3125352482453400.01987497669606.282965836
#Sta/Elev= 30
       0 1464.53    34.4 1457.66    88.9 1445.14    99.3 1439.98   112.3 1436.22
   129.5 1434.44   164.6 1433.73   168.9  1432.9  173.781430.238   177.5 1428.46
   181.8 1428.15  189.391430.237   199.1  1435.8   216.2  1440.4   229.3 1439.31
     259 1446.34   262.4 1448.12   265.5 1450.95   274.7 1462.18   283.9  1470.1
   302.6 1481.52   332.3 1497.04   354.4 1509.74   396.1 1536.76   416.3 1548.37
   477.9 1587.31   524.9 1618.79   543.2 1632.39   573.2 1652.58589.8615 1666.56
#Mann= 3 , 0 , 0
       0     .12       0  173.78    .045       0  189.39     .12       0
Bank Sta=173.78,189.39
XS Rating Curve= 0 ,0
Exp/Cntr(USF)=0,0
Exp/Cntr=0.3,0.1

Type RM Length L Ch R = 1 ,1198    ,138.2,137.7,134.7
XS GIS Cut Line= 4
2453614.32933222670237.8118983852453580.13101458670107.858291326
2453486.65561301669847.9510772092453461.57684673669615.402517209
#Sta/Elev= 30
       0 1537.26    80.6    1482   135.4 1446.69   152.4 1433.94   165.2 1423.37
   169.4  1421.3   177.9 1420.41  185.311417.129   190.7  1415.3   194.9 1414.84
   205.7 1417.13   250.2 1424.76   262.9  1430.4   320.7 1450.66   352.2  1465.8
   369.2 1477.99   390.5 1494.66   427.7 1522.29   455.9 1540.71     476 1554.77
   484.1 1559.38   515.6 1582.99   536.4 1596.14   547.2 1603.87   565.2 1617.38
   584.6 1634.15   608.8 1648.16   620.9 1658.25   636.9 1675.37644.4804 1680.93
#Mann= 3 , 0 , 0
       0     .12       0  185.31    .045       0   205.7     .12       0
Bank Sta=185.31,205.7
XS Rating Curve= 0 ,0
Exp/Cntr(USF)=0,0
Exp/Cntr=0.3,0.1

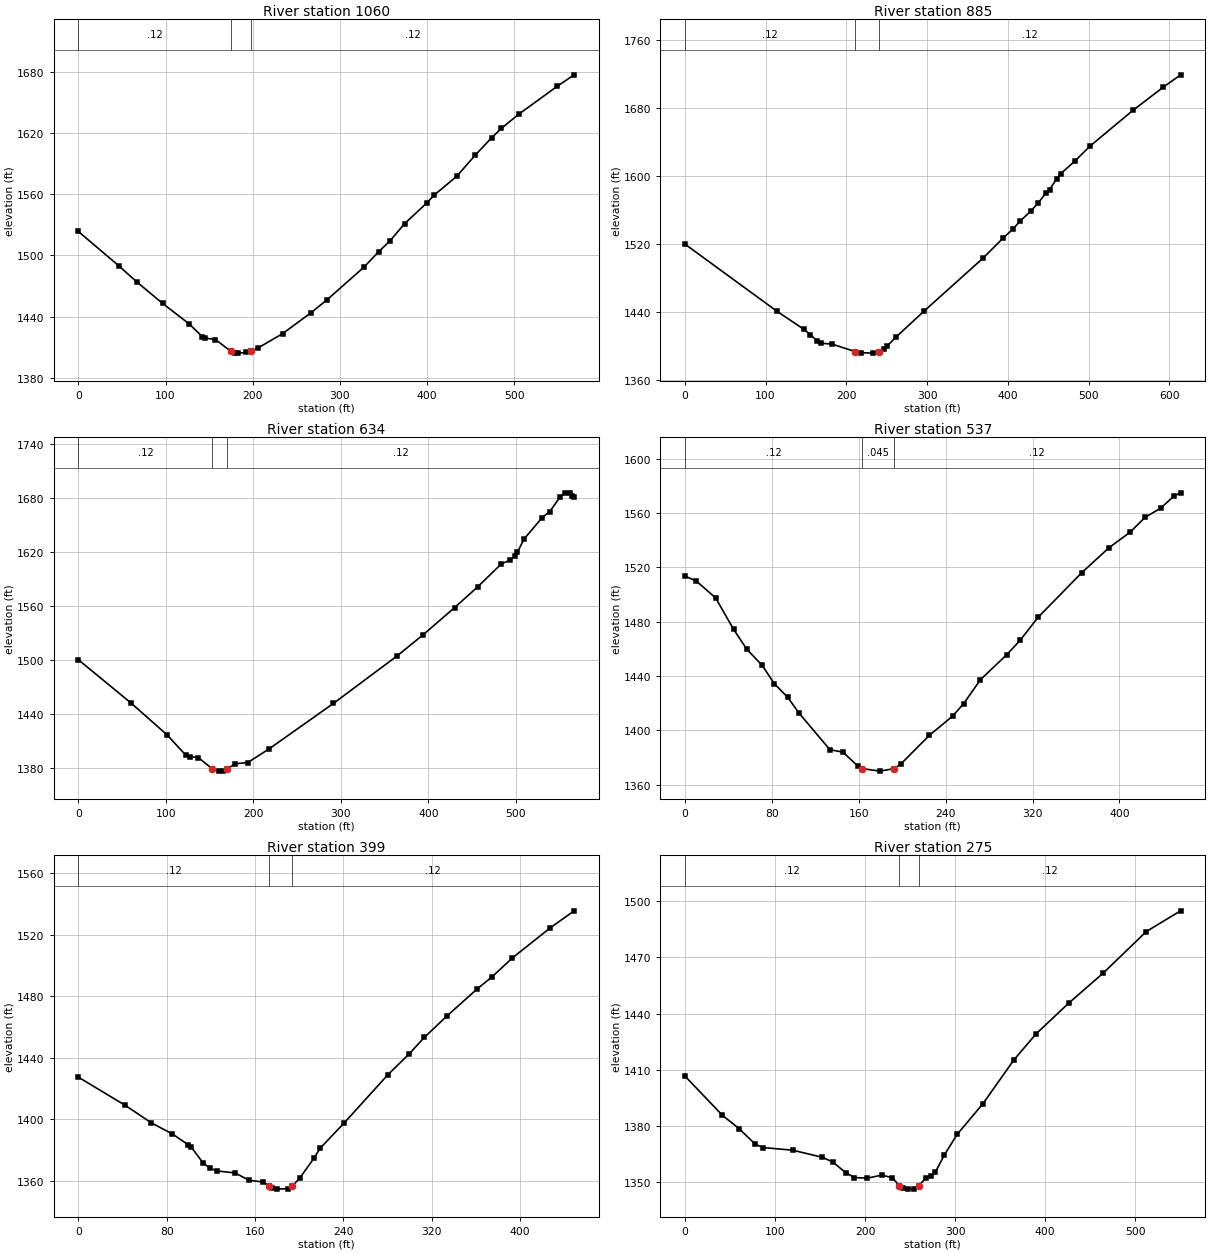
Type RM Length L Ch R = 1 ,1060    ,178.3,175.1,179.2
XS GIS Cut Line= 4
2453744.28293928670171.6951509342453710.08462164670055.420870934
2453641.68798634 669907.228161132453543.65280909669640.481283483
#Sta/Elev= 30
       0  1523.4    46.7 1489.49    67.5 1473.62    96.7 1452.82   127.1 1432.79
   142.2 1420.24   145.2 1418.94   157.3  1417.4   174.71406.072   179.1  1404.5
   183.5 1404.13   192.3 1404.76  197.971406.075   205.5 1408.93   234.2 1423.21
   267.2 1443.95   284.8 1456.11   327.4 1488.27   344.4 1503.51   357.2 1513.98
   374.2 1531.07   399.8 1551.47     408 1558.99   433.9 1577.42   455.2 1598.22
   473.9 1615.16   485.1  1624.4   505.1 1638.33   549.5 1665.89568.6058 1676.92
#Mann= 3 , 0 , 0
       0     .12       0   174.7    .045       0  197.97     .12       0
Bank Sta=174.7,197.97
XS Rating Curve= 0 ,0
Exp/Cntr(USF)=0,0
Exp/Cntr=0.3,0.1

Type RM Length L Ch R = 1 ,885     ,249.2,251.2,249.1
XS GIS Cut Line= 4
2453917.55441536670148.8962725032453874.23654634669991.584011326
2453726.04383654669722.5572458362453659.92708909 669594.88352662
#Sta/Elev= 30
       0 1520.24   114.1 1441.28   147.1 1420.25   155.6 1413.84     164 1406.15
   169.2 1403.61   182.2 1402.74  211.411393.757   218.8 1392.59   232.5 1392.07
  240.661393.755   246.2 1396.79   250.7 1400.44   261.6 1410.96   296.4 1441.48
   369.4 1503.62   394.2 1527.19     406 1537.37   415.1 1546.98   428.8  1559.1
     438 1568.84   447.1 1579.89   451.7 1584.06   460.7 1596.97   465.4 1602.67
   483.4 1617.84   501.5 1634.93   555.5 1677.56   592.6 1704.43   614.1 1718.93
#Mann= 3 , 0 , 0
       0     .12       0  211.41    .045       0  240.66     .12       0
Bank Sta=211.41,240.66
XS Rating Curve= 0 ,0
Exp/Cntr(USF)=0,0
Exp/Cntr=0.3,0.1

Type RM Length L Ch R = 1 ,634     ,96.9,96.7,95.8
XS GIS Cut Line= 4
 2454152.3828632670028.062216817 2454104.5052185 669914.06782466
2454026.98903183669795.5136568172453794.44047183669604.003077993
#Sta/Elev= 30
       0 1500.15    60.2 1451.96   101.1 1416.76   122.7 1393.97   127.4 1392.36
     137 1391.28  153.261378.581   160.9 1376.13   165.7 1376.45  169.991378.581
   179.2 1384.23   193.7 1385.72   218.2 1401.03   291.5 1451.51   364.1 1504.26
   393.8 1527.79   429.9 1558.09   456.3 1581.25   483.2 1606.67   493.6 1611.25
   498.8 1615.36   501.8 1619.89   509.1 1634.17   529.9 1658.25   538.7 1665.09
   550.6 1681.46   555.7 1685.33     562 1685.89   564.3 1682.37566.5434 1681.17
#Mann= 3 , 0 , 0
       0     .12       0  153.26    .045       0  169.99     .12       0
Bank Sta=153.26,169.99
XS Rating Curve= 0 ,0
Exp/Cntr(USF)=0,0
Exp/Cntr=0.3,0.1

Type RM Length L Ch R = 1 ,537     ,137.3,138.1,134.8
XS GIS Cut Line= 4
 2454262.6602233669969.2566656132454190.04336735669861.876421172
2454084.98068214669731.3205844062453976.82791796669614.670103036
#Sta/Elev= 30
       0 1513.57    10.3 1510.13    28.4 1497.49    44.9 1474.35      57 1459.82
    71.3 1447.78    82.3 1434.45    94.6 1424.41   105.3 1412.56   133.5  1385.8
   145.5 1384.01   159.1 1373.83  163.531371.822   179.6    1370  192.491371.822
   198.7 1375.14   225.1 1396.37   246.4 1410.47   256.7 1419.73   272.1 1437.34
   296.3 1455.72   308.7 1466.38   325.1 1483.22   365.2 1515.98   390.5 1534.57
   409.5 1545.67   423.6 1556.84   437.8 1563.52   450.5 1572.69   456.3 1574.87
#Mann= 3 , 0 , 0
       0     .12       0  163.53    .045       0  192.49     .12       0
Bank Sta=163.53,192.49
XS Rating Curve= 0 ,0
Exp/Cntr(USF)=0,0
Exp/Cntr=0.3,0.1

Type RM Length L Ch R = 1 ,399     ,125.2,124.2,123.4
XS GIS Cut Line= 4
2454387.21131105 669870.749955642454298.29568517669772.714778385
2454188.86106869669661.0002740712454042.94824673 669594.88352662
#Sta/Elev= 30
       0 1427.44    42.4 1409.13    66.2 1397.68    85.2 1390.47    99.3 1383.58
   102.2 1381.94   113.2 1371.45   119.2 1368.23   125.7 1366.41   141.8 1365.14
   154.6 1360.38   167.3 1359.19  173.041356.434   175.8 1355.13   179.7 1354.59
   189.9  1354.9  193.451356.437   200.3 1361.54   213.3  1374.7   218.9 1381.15
   240.3 1397.34   280.3 1429.04   299.8 1442.75   313.2 1453.28   334.2 1467.54
   361.4 1485.03   374.5 1492.66   393.1 1505.07   427.2 1524.53448.9293 1535.66
#Mann= 3 , 0 , 0
       0     .12       0  173.04    .045       0  193.45     .12       0
Bank Sta=173.04,193.45
XS Rating Curve= 0 ,0
Exp/Cntr(USF)=0,0
Exp/Cntr=0.3,0.1

Type RM Length L Ch R = 1 ,275     ,141,140.5,138.8
XS GIS Cut Line= 4
2454533.12413301669795.5136568172454432.80906791669704.318143091
2454270.93703105 669594.883526622454077.14656438669492.288573679
#Sta/Elev= 30
       0 1406.67    41.8 1385.62    60.4 1378.49    78.2 1370.19    87.1 1368.43
   119.9    1367   152.5 1363.25     164 1360.79   178.4  1355.1   188.1 1352.42
   202.4 1352.08   218.7 1353.72   230.3 1352.32  238.021348.112   241.8 1346.68
   247.6 1346.23   253.9 1346.49  259.581348.112   267.7 1352.24   273.5 1353.35
   278.1 1355.34   288.1 1364.53   302.2 1375.45     331 1391.93   365.1 1415.18
     390 1429.23   426.2 1445.62   464.3 1461.58   512.2 1483.81550.2377 1494.85
#Mann= 3 , 0 , 0
       0     .12       0  238.02    .045       0  259.58     .12       0
Bank Sta=238.02,259.58
XS Rating Curve= 0 ,0
Exp/Cntr(USF)=0,0
Exp/Cntr=0.5,0.3

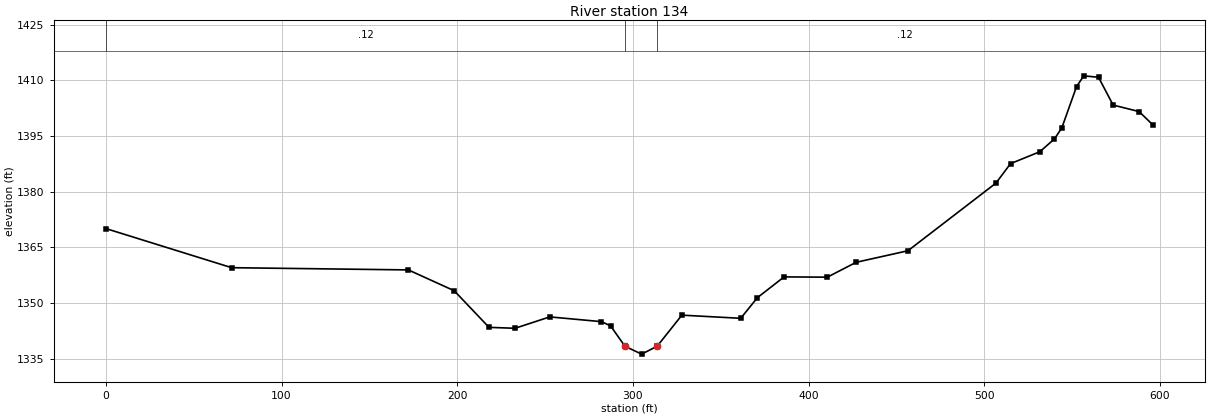
Type RM Length L Ch R = 1 ,134     ,134,134,134
XS GIS Cut Line= 4
2454651.67830085669727.1170215222454517.16491811669599.443302307
2454334.77389066669467.2098074052454156.94263889669414.772387012
#Sta/Elev= 30
       0 1370.04    71.6 1359.49   172.2 1358.89   198.3 1353.27   218.1  1343.4
   232.9 1343.15   252.7 1346.22   282.1 1344.94   287.3 1343.81   295.51338.298
     305 1336.18   313.81338.299   327.9 1346.69   361.4 1345.84   370.9 1351.41
   386.1 1357.01   410.7 1356.93   427.1 1360.94   456.6 1364.06   506.7  1382.3
     515 1387.55   531.7 1390.76     540 1394.22   544.2 1397.19   552.6 1408.35
   556.7 1411.23   565.1 1410.84   573.4 1403.35   588.2 1401.59596.1411 1397.95
#Mann= 3 , 0 , 0
       0     .12       0   295.5    .045       0   313.8     .12       0
Bank Sta=295.5,313.8
XS Rating Curve= 0 ,0
Exp/Cntr(USF)=0,0
Exp/Cntr=0.5,0.3
LCMann Table=0

Chan Stop Cuts=-1
Use User Specified Reach Order=0
Composite Channel Slope=5